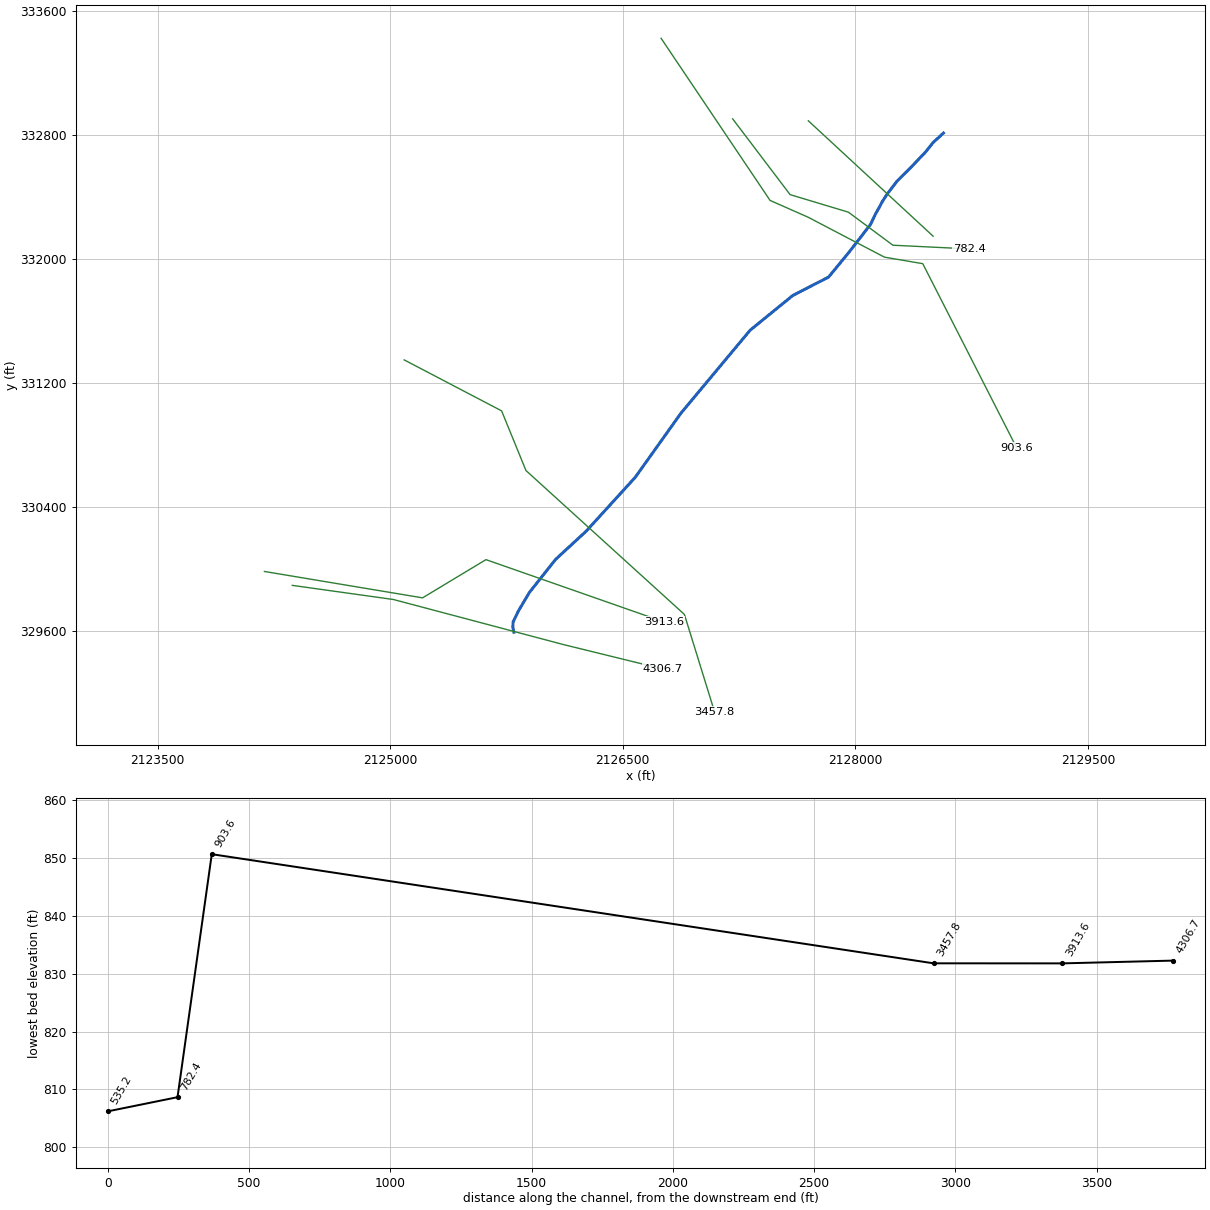
--- CABINRN.prj (project) ---

Proj Title=CABINRN
Current Plan=p01
Default Exp/Contr=0,0
English Units
Geom File=g01
Flow File=f01
Plan File=p01
BEGIN DESCRIPTION:
END DESCRIPTION:
DSS Export Rating Curves= 0
DSS Export Rating Curve Sorted= 0
DSS Export Volume Flow Curves= 0
DXF OffsetX= 0
DXF OffsetY= 0
DXF ScaleX= 0
DXF ScaleY= 0

--- CABINRN.p01 (plan) ---

Plan Title=Floodplain
Program Version=4.00
Geom File=g01
Flow File=f01
K Sum by GR=0
Std Step Tol=0.01
Critical Tol=0.01
Num of Std Step Trials=20
Max Error Tol=0.3
Flow Tol Ratio=0.001
Split Flow NTrial=30
Split Flow Tol=0.02
Split Flow Ratio=0.02
Log Output Level=0
Friction Slope Method=1
Unsteady Friction Slope Method=2
Unsteady Bridges Friction Slope Method=1
Global Log Level=0
CheckData=False
Run HTab=0
Run UNet=0
Run PostProcess=0
UNET Theta=0
UNET Theta Warmup=0
UNET ZTol=0
UNET ZSATol=0
UNET MxIter=0
UNET MaxInSteps=0
UNET DtIC=0
UNET DtMin=0
UNET MaxCRTS=0
UNET WFStab=0
UNET SFStab=0
UNET WFX=0
UNET SFX=0
UNET DSS MLevel=0
UNET DZMax Abort=0
UNET Convert EG Bridges=0
UNET Use Existing IB Tables=0
UNET Froude Limit=0
UNET Froude Power=0
Write IC File=0
Echo Input=False
Echo Output=False
Write Detailed=0

--- CABINRN.f01 (steady flow) ---

Flow Title=NFF Regression Equation
Program Version=4.00
Number of Profiles= 1
Profile Names=P100yr
River Rch & RM=CABINRN,Main            ,4306.7
     907
River Rch & RM=CABINRN,Main            ,3457.8
     980
River Rch & RM=CABINRN,Main            ,3457.8
    1075
River Rch & RM=CABINRN,Main            ,903.6
    1256
River Rch & RM=CABINRN,Main            ,535.2
    1254
Boundary for River Rch & Prof#=CABINRN,Main            , 1
Up Type= 0
Dn Type= 1
Dn Known WS=814.05
DSS Import GetInterval= 0
DSS Import GetPeak= 0
DSS Import FillOption= 0

--- CABINRN.g01 (geometry) ---

Geom Title=USGS 10m DEM
Program Version=4.00

River Reach=CABINRN         ,Main
Reach XY= 26
     2125798.379      329589.608     2125791.468      329619.424
     2125792.858      329654.969     2125804.691      329679.405
     2125825.592      329723.621     2125897.822      329845.878
     2126066.797      330059.407     2126264.964      330242.758
     2126580.373      330589.593     2126776.316      330864.956
     2126875.706      331004.631     2127321.502      331540.183
     2127596.704      331764.673      2127827.74       331883.85
     2127959.868      332044.884     2128097.717      332223.374
     2128131.382      332293.011     2128153.676      332333.207
     2128156.954       332339.15     2128176.101       332374.93
     2128206.361      332421.098      2128268.84      332503.251
     2128359.261      332593.273     2128451.441       332689.84
     2128502.948      332754.095      2128568.55      332813.858

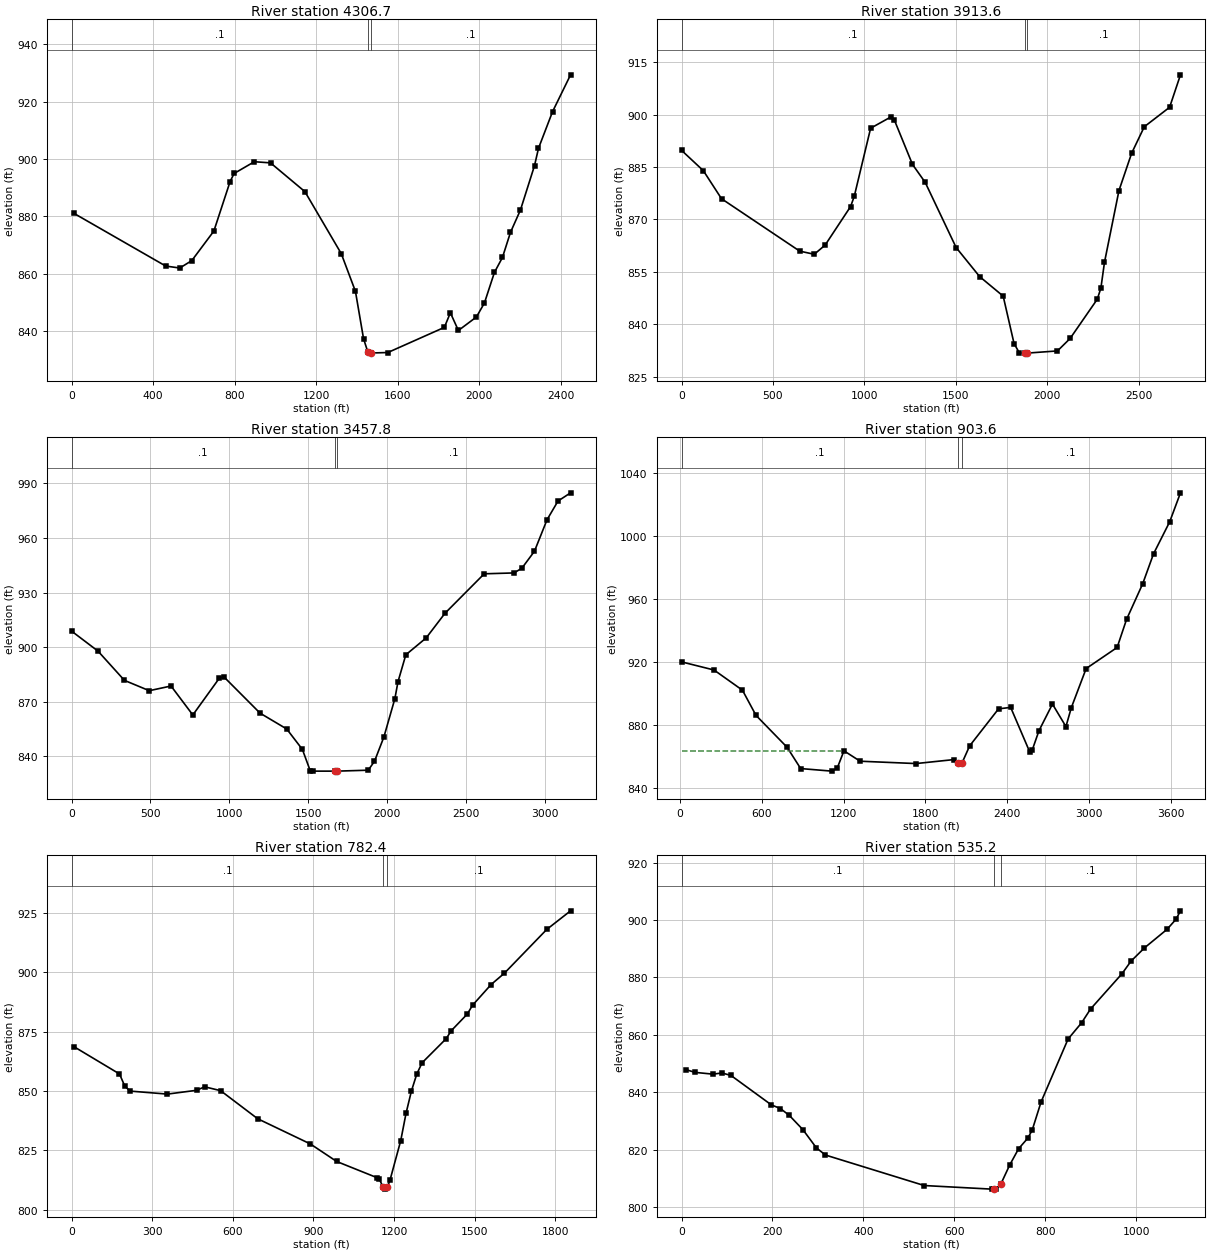
Type RM Length L Ch R = 1 ,4306.7  ,393.8,393.1,392.4
XS GIS Cut Line= 4
     2124368.977      329891.898     2125021.246      329800.581
     2126115.013      329510.134     2126754.684      329352.756
#Sta/Elev= 30
     9.8   881.1     462  862.64   530.8  861.96   589.8  864.54   698.3  874.87
   777.8  892.12   797.6  894.96   896.9  899.06   976.3  898.66  1145.1  888.62
  1323.7  866.96  1393.2   853.8  1432.9  837.31    1454  832.63  1462.7  832.25
    1469  832.29  1552.1  832.46  1829.6  841.24  1859.1  846.34  1898.5  840.15
  1986.9  844.86  2026.3  849.75  2075.4  860.43  2114.8  865.65  2154.1  874.39
  2203.2  882.23  2272.1  897.68  2291.7  903.75  2360.6  916.52  2449.1  929.39
#Mann= 3 , 0 , 0
       0      .1       0    1454    .045       0    1469      .1       0
Bank Sta=1454,1469
XS Rating Curve= 0 ,0
Exp/Cntr=0.3,0.1

Type RM Length L Ch R = 1 ,3913.6  ,465.1,455.8,446.5
XS GIS Cut Line= 4
     2124189.263      329981.756     2125209.081      329811.236
     2125617.991      330058.134      2126766.08      329655.506
#Sta/Elev= 30
       0  889.77   119.3  883.95   218.7  875.93   646.2  860.94   725.8  860.04
   785.4  862.67   924.6   873.7   944.5   876.6    1034  896.09  1143.4  899.27
  1163.3   898.5  1262.9  885.74  1332.5   880.6  1501.7  861.96  1630.3  853.65
  1758.9  848.07  1818.3  834.52    1848  831.77  1875.6  831.78  1890.6  831.78
  2055.7   832.4  2124.9  835.96  2273.3  847.18  2293.1  850.35  2312.8  857.74
    2392  878.27  2461.2  888.93  2530.5  896.51  2668.9  902.08  2728.3  911.36
#Mann= 3 , 0 , 0
       0      .1       0  1875.6    .045       0  1890.6      .1       0
Bank Sta=1875.6,1890.6
XS Rating Curve= 0 ,0
Exp/Cntr=0.3,0.1

Type RM Length L Ch R = 1 ,3457.8  ,2547.9,2554.2,2560.4
XS GIS Cut Line= 5
     2125090.614      331348.609     2125718.831      331019.356
     2125875.948      330633.866     2126897.768      329704.119
     2127091.729      329076.258
#Sta/Elev= 30
       0  908.78   167.5  897.77   334.9   881.7   492.5  876.02   630.5   878.6
   768.7  862.67   937.2  882.95     967  883.52  1195.1  863.67  1364.1  854.96
  1463.5  843.72  1513.2  831.98    1533  831.78    1669  831.78    1684  831.78
  1880.9  832.29  1920.7  837.18  1980.3  850.53  2049.9   871.6  2069.7   880.9
  2119.4  895.75  2248.6  905.06  2367.9  918.61  2616.6  940.31  2805.7  940.79
  2855.5   943.4  2935.2  952.71  3014.8  970.02  3084.5  980.33  3164.2  984.85
#Mann= 3 , 0 , 0
       0      .1       0    1669    .045       0    1684      .1       0
Bank Sta=1669,1684
XS Rating Curve= 0 ,0
Exp/Cntr=0.3,0.1

Type RM Length L Ch R = 1 ,903.6   ,125.1,121.2,117.3
XS GIS Cut Line= 6
     2126747.254      333426.556       2127450.3      332378.835
     2127695.448      332270.406     2128187.785      332012.376
     2128434.876      331970.285     2129040.483      330780.627
#Sta/Elev= 30
     9.9  920.06   248.4  914.89     457  902.06   556.4  886.07   784.9  865.75
   884.2  852.25  1112.7  850.62  1152.5  852.55  1202.1  863.52 1320.64  856.92
 1730.94  855.43  2009.4  857.96    2038  855.47  2066.7   855.5  2124.3  866.67
  2336.4   890.2  2425.4  891.12  2563.9  863.09  2583.6  864.01  2633.1  876.32
    2732  893.23  2830.9  878.93  2870.4  890.94  2979.2  915.81  3206.6  929.22
  3275.8  947.06  3394.5  969.76  3473.6  988.71  3592.3 1009.08  3671.4  1027.5
#Mann= 3 , 0 , 0
     9.9      .1       0    2038    .045       0  2066.7      .1       0
#XS Ineff= 2 , 0
         1201.55  863.46
Permanent Ineff=
       F       F
Bank Sta=2038,2066.7
XS Rating Curve= 0 ,0
Exp/Cntr=0.3,0.1

Type RM Length L Ch R = 1 ,782.4   ,249.7,247.3,244.8
XS GIS Cut Line= 5
      2127209.08      332905.609     2127579.545      332416.175
     2127955.185      332303.001     2128242.377      332089.447
     2128734.644      332065.622
#Sta/Elev= 30
     9.9  868.62   178.2   857.2     198  852.05   217.8  849.98   356.4  848.72
   465.3  850.32     495  851.79   554.4  850.17   692.3  838.34   888.5  827.71
   986.5  820.32  1135.4  813.55  1145.3  812.78  1160.2  809.38  1165.2  808.67
  1175.2  809.49  1185.1  812.54  1224.9  829.13  1244.7  840.68  1264.6  850.01
  1284.5  857.14  1304.4  861.92  1393.6  872.03  1413.3  875.48  1472.5  882.44
  1492.2  886.17  1561.2  894.89  1610.5  899.65  1768.2   918.1  1856.9  925.95
#Mann= 3 , 0 , 0
       0      .1       0  1160.2    .045       0  1175.2      .1       0
Bank Sta=1160.2,1175.2
XS Rating Curve= 0 ,0
Exp/Cntr=0.3,0.1

Type RM Length L Ch R = 1 ,535.2   ,537.1,535.2,533.3
XS GIS Cut Line= 2
     2127697.014      332893.256     2128501.753      332147.734
#Sta/Elev= 30
     9.9  847.86    29.6  846.91    69.2  846.29    88.9   846.7   108.7  845.84
   197.7  835.56   217.4  834.31   237.2  831.88   266.8  826.96   296.5  820.61
   316.3  818.11   533.7  807.47   681.9  806.22     687  806.25   691.8  806.29
     702  807.97   721.5  814.61   741.2  820.32     761  823.92   770.9  826.74
   790.6  836.64   849.9  858.54   879.6  864.18   899.3  868.99   968.5   881.3
   988.3  885.68  1017.9   890.3  1067.4  896.75  1087.1  900.26    1097  903.21
#Mann= 3 , 0 , 0
       0      .1       0     687    .045       0     702      .1       0
Bank Sta=687,702
XS Rating Curve= 0 ,0
Exp/Cntr=0.3,0.1

Chan Stop Cuts=-1
Use User Specified Reach Order=0